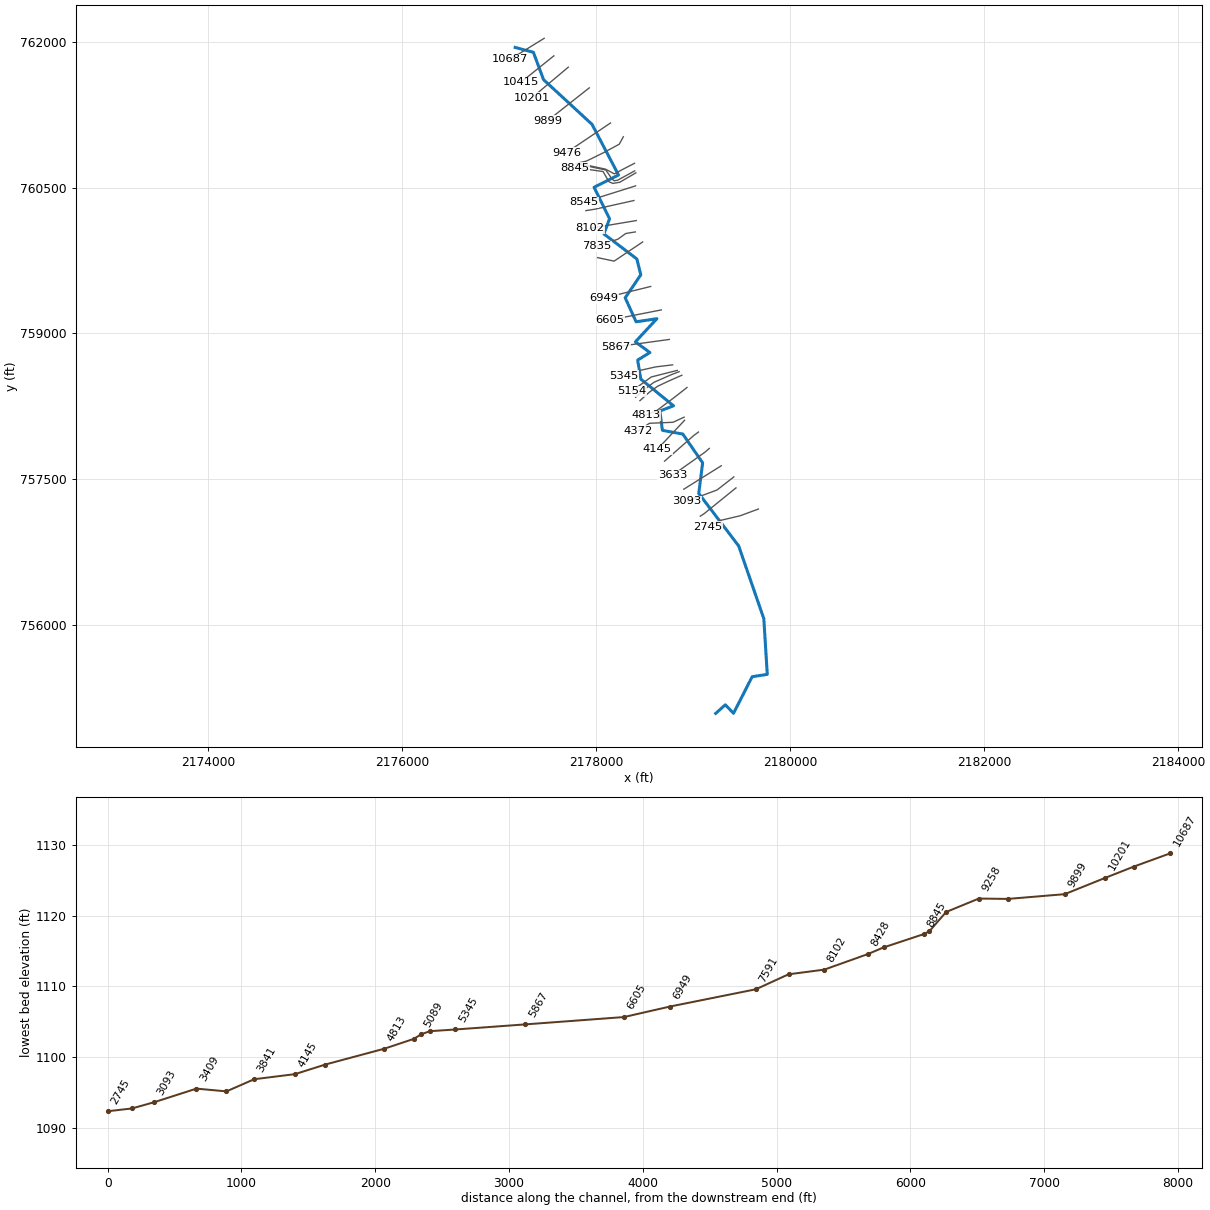
--- HACKCKT2.prj (project) ---

Proj Title=HACKCKT2
Current Plan=p01
Default Exp/Contr=0.3,0.1
English Units
Geom File=g01
Flow File=f01
Plan File=p01
Y Axis Title=Elevation
X Axis Title(PF)=Main Channel Distance
X Axis Title(XS)=Station
BEGIN DESCRIPTION:
---------- MODELED AS PART OF WVEMD CTP PROGRAM, 2023----------
Stream Name: Hackers Creek Tributary 2
Flood Zone:  AFH
Upshur County, WV
HEC-RAS Version: RAS 6.3
Vertical Datum: NAVD88
Projection: NAD 1983 StatePlane West Virginia S FIPS 4702 (US Feet)
Terrain: 1-meter LIDAR (FEMA Region III 3DEP collected 2016-2018)
Land Use: 2019 NLCD
Hydrologic Method:
WV SIR2010-5033 regression equations
Additional Model Notes:
None
END DESCRIPTION:
DSS File=dss
DSS Export Rating Curves= 0
DSS Export Rating Curve Sorted= 0
DSS Export Volume Flow Curves= 0
DXF OffsetX= 0
DXF OffsetY= 0
DXF ScaleX= 1
DXF ScaleY= 10

--- HACKCKT2.p01 (plan) ---

Plan Title=Floodplain
Program Version=6.30
Short Identifier=Floodplain
Geom File=g01
Flow File=f01
Subcritical Flow
K Sum by GR= 0
Std Step Tol= 0.01
Critical Tol= 0.01
Num of Std Step Trials= 20
Max Error Tol= 0.3
Flow Tol Ratio= 0.001
Split Flow NTrial= 30
Split Flow Tol= 0.02
Split Flow Ratio= 0.02
Log Output Level= 0
Friction Slope Method= 1
Unsteady Friction Slope Method= 2
Unsteady Bridges Friction Slope Method= 1
Parabolic Critical Depth
Global Vel Dist= 0 , 0 , 0
Global Log Level= 0
CheckData=True
Encroach Param=-1 ,0,0, 0
Computation Interval=1MIN
Output Interval=1HOUR
Instantaneous Interval=1HOUR
Mapping Interval=1HOUR
Computation Time Step Use Courant=        0
Computation Time Step Use Time Series=    0
Computation Time Step Count To Double=0
Computation Time Step Max Doubling=0
Computation Time Step Max Halving=0
Computation Time Step Residence Courant=0
Run HTab= 0
Run UNet= 0
Run Sediment= 0
Run PostProcess= 0
Run WQNet= 0
Run RASMapper= 0
UNET Theta= 1
UNET Theta Warmup= 1
UNET ZTol= 0.02
UNET ZSATol= 0.02
UNET MxIter= 20
UNET Max Iter WO Improvement= 0
UNET MaxInSteps= 0
UNET DtIC= 0
UNET DtMin= 0
UNET MaxCRTS= 20
UNET WFStab= 2
UNET SFStab= 1
UNET WFX= 1
UNET SFX= 1
UNET Gravity=32.17405
UNET 1D Methodology=Finite Difference
UNET DSS MLevel= 4
UNET Pardiso=0
UNET DZMax Abort= 100
UNET Use Existing IB Tables=-1
UNET Froude Reduction=False
UNET Froude Limit= 0.8
UNET Froude Power= 4
UNET D1 Cores= 0
UNET WindReference=Eulerian
UNET WindDragFormulation=Hsu (1988)
UNET D2 Coriolis=0
UNET D2 Cores= 0
UNET D2 Theta= 1
UNET D2 Theta Warmup= 1
UNET D2 Z Tol= 0.01
UNET D2 Volume Tol= 0.01
UNET D2 Max Iterations= 20
UNET D2 Equation= 0
UNET D2 RampUpFraction=0.1
UNET D2 TimeSlices= 1
UNET D2 Turbulence Formulation=None
UNET D2 Eddy Viscosity=0.3
UNET D2 Transverse Eddy Viscosity=0.1
UNET D2 Smagorinsky Mixing=0.05
UNET D2 BCVolumeCheck=0
UNET D2 Cores=0
UNET D2 SolverType=PARDISO (Direct)
UNET D2 Minimum Iterations= 3
UNET D2 Maximum Iterations= 30
UNET D2 Restart Number= 10
UNET D2 Relaxation Coeff=1.3
UNET D2 SOR Precondition Iterations= 10
UNET D2 ILUT Maximum Fill= 8
UNET D2 ILUT Tolerance=1E-08
UNET D2 Convergence Tolerance=0.00001
UNET D1D2 MaxIter= 0
UNET D1D2 ZTol=0.01
UNET D1D2 QTol=0.1
UNET D1D2 MinQTol=1
DSS File=dss
Write IC File= 0
Write IC File at Fixed DateTime=0
Write IC File at Sim End=0
Echo Input=False
Echo Parameters=False
Echo Output=False
Write Detailed= 0
HDF Write Warmup=0
HDF Write Time Slices=0
HDF Flush=0
HDF Compression= 1
HDF Chunk Size= 1
HDF Spatial Parts= 1
HDF Use Max Rows=0
HDF Fixed Rows= 1
Calibration Method= 0
Calibration Iterations= 20
Calibration Max Change=0.05
Calibration Tolerance=0.2
Calibration Maximum=1.5
Calibration Minimum=0.5
Calibration Optimization Method= 1
WQ AD Non Conservative
WQ ULTIMATE=-1
WQ Max Comp Step=1HOUR
WQ Output Interval=15MIN
WQ Output Selected Increments= 0
WQ Output face flow=0
WQ Output face velocity=0
WQ Output face area=0
WQ Output face dispersion=0
WQ Output cell volume=0
WQ Output cell surface area=0
WQ Output cell continuity=0
WQ Output cumulative cell continuity=0
WQ Output face conc=0
WQ Output face dconc_dx=0
WQ Output face courant=0
WQ Output face peclet=0
WQ Output face adv mass=0
WQ Output face disp mass=0
WQ Output cell mass=0
WQ Output cell source sink temp=0
WQ Output nsm pathways=0
WQ Output nsm derived pathways=0
WQ Create Restart=0
WQ Fixed Restart=0
WQ System Summary=0
WQ Write To DSS=0
Sorting and Armoring Iterations= 10
XS Update Threshold= 0.02
Bed Roughness Predictor= 0
Hydraulics Update Threshold= 0.02
Energy Slope Method= 1
Volume Change Method= 1
Sediment Retention Method= 0
Sediment TS Multiplier= 1
Warm Up Method= 0
XS Weighting Method= 0
Number of US Weighted Cross Sections= 1
Number of DS Weighted Cross Sections= 1
Upstream XS Weight=0
Main XS Weight=1
Downstream XS Weight=0
Number of DS XS's Weighted with US Boundary= 1
Upstream Boundary Weight= 1
Weight of XSs Associated with US Boundary= 0
Number of US XS's Weighted with DS Boundary= 1
Downstream Boundary Weight= 0.5
Weight of XSs Associated with DS Boundary= 0.5
Percentile Method= 0
Sediment Output Level= 3
Mass or Volume Output= 0
Output Increment Type= 1
Profile and TS Output Increment= 1
Transport Output Increment 1
XS Output Flag= 0
XS Output Increment= 10
Read HDF5 Sediment Hotstart= 0
Sediment Hotstart Type= 0
Write Gradation File= 0
Read Gradation Hotstart= 0
Write HDF5 File= 1
Write Binary Output= 1
Write DSS Sediment File= 0
DSS Sediment Output Type= 1
SV Curve= 0
Specific Gage Flag= 0
Subcell Erosion Methods= 0
Subcell Deposition Methods= 0
Advection Scheme= 1
Matrix Solver= 0
Implicit Weighting Factor= 1
Maximum Outer Loop Convergence Iterations= 5
Convergence Maximum Absolute= 0.001
Convergence RMSE= 0.0001
Grain Fractions Max Abs Error= 0.001
Max Subgrid Regions= 1
Max Subgrid Length Scale= 3.402823E+38
Initial Layer Thickness= 3.402823E+38
Min Layer Thickness= 3.402823E+38
Max Layer Thickness= 3.402823E+38
Number of Layers= 5

--- HACKCKT2.f01 (steady flow) ---

Flow Title=Flow
Program Version=6.30
Number of Profiles= 1
Profile Names=01pct
River Rch & RM=River,Reach,10687
     748
River Rch & RM=River,Reach,7835
     847
River Rch & RM=River,Reach,5089
     969
Boundary for River Rch & Prof#=River,Reach           , 1
Up Type= 0
Dn Type= 3
Dn Slope=0.0025
DSS Import GetInterval= 0
DSS Import GetPeak= 0
DSS Import FillOption= 0

--- HACKCKT2.g01 (geometry) ---

Geom Title=Geometry
Program Version=6.30

River Reach=River           ,Reach
Reach XY= 30
2177162.51303992761940.8255888372177350.40833342761890.517946675
2177454.80084117 761609.505057262177955.01539193761149.582420677
2178228.13033126 760629.050325262177976.10557283760502.251038179
 2178135.5274981760178.5997825862178077.57945126   760022.125358
2178417.16997942759765.2361080052178457.74831034759601.979544759
2178296.69515476759365.4363826662178409.58666126759118.648818508
2178623.60887101759150.4702771752178401.91771334758912.210255012
2178551.75304359758802.2088345892178425.46884733758724.830052346
2178458.57803309758528.2641725092178795.56456384758254.348053679
2178654.77186643758201.4078708442178680.29773401758002.209122255
2178891.17198418757963.5484384152179095.26409568757667.912546754
2179055.37277126 757352.903334262179467.10554358756812.854873672
2179726.34124559756064.2215284262179761.88284117755491.950691342
2179606.26701067755467.7985086742179414.10794617755091.893748671
2179329.03134467755178.8302545852179230.59092475755090.577478334

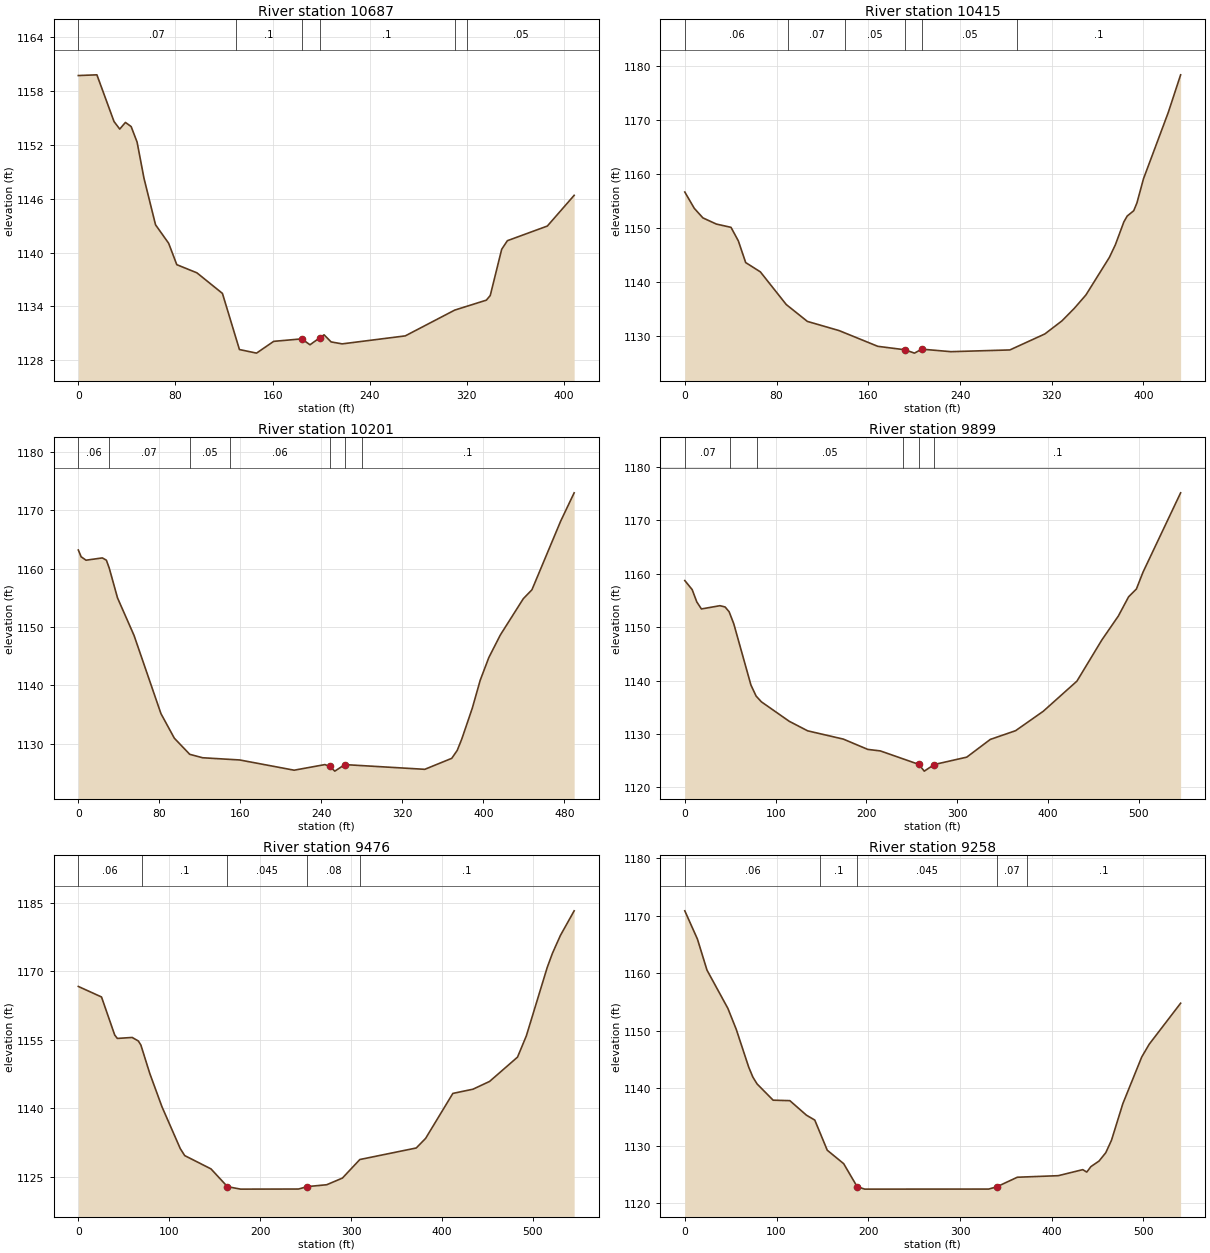
Type RM Length L Ch R = 1 ,10687   ,259.3,272.2,264.8
XS GIS Cut Line= 2
2177461.24965752762034.5140047032177113.33318772761820.592391517
#Sta/Elev= 30
       0 1159.71    15.3 1159.79    29.4 1154.59    34.1 1153.75    38.8 1154.49
    43.5 1154.03    48.4  1152.3    54.1 1148.26    63.6 1143.09    74.4 1141.03
    81.1 1138.65    97.7 1137.74   118.7 1135.45   132.7  1129.2   146.8  1128.8
   160.9 1130.11     1841130.388   190.8 1129.73   198.7 1130.49   202.4 1130.84
   208.2 1130.05   217.3 1129.83   269.3 1130.72     310 1133.59   336.1  1134.7
   339.3 1135.22   348.7 1140.36   353.4 1141.32   386.3 1142.95   408.4 1146.37
#Mann= 6 ,-1,0
       0     .07       0     130      .1       0     184    .045       0
   198.7      .1       0     310     .07       0     320     .05       0
Bank Sta=184,198.7
XS Rating Curve= 0 ,0
Exp/Cntr(USF)=0,0
Exp/Cntr=0.3,0.1

Type RM Length L Ch R = 1 ,10415   ,211.1,213.5,210.7
XS GIS Cut Line= 2
2177561.21839917761854.3861197992177223.72780607761584.065984555
#Sta/Elev= 30
       0 1156.74     8.3 1153.71    15.8 1151.95    27.5 1150.81    40.3  1150.2
    46.7 1147.69    53.1 1143.68    65.9 1141.96    88.5 1135.91   106.9 1132.79
   134.6 1131.09   168.3 1128.18   191.91127.542   200.3 1126.92   206.61127.655
   232.1 1127.19   283.5 1127.51     314 1130.47   328.9 1132.89   339.6 1135.19
   349.8 1137.68   370.3 1144.65   375.5 1146.98   382.9 1151.21   385.8 1152.29
   391.5 1153.28   394.3 1154.72     400 1159.18   421.6 1171.45   432.4 1178.43
#Mann= 6 ,-1,0
       0     .06       0      90     .07       0     140     .05       0
   191.9    .045       0   206.6     .05       0     290      .1       0
Bank Sta=191.9,206.6
XS Rating Curve= 0 ,0
Exp/Cntr(USF)=0,0
Exp/Cntr=0.3,0.1

Type RM Length L Ch R = 1 ,10201   ,300,301.8,297.4
XS GIS Cut Line= 2
2177710.30404951761738.0665464522177335.13246787761423.512207258
#Sta/Elev= 30
       0  1163.2     2.8 1162.04     7.6 1161.46    23.7 1161.85    27.7 1161.46
    30.5 1160.12    38.7    1155      55 1148.58    81.6 1135.17    94.8 1130.97
     110 1128.21   122.8 1127.62   159.4 1127.24   213.1 1125.49   243.5 1126.45
   248.2 1126.13   253.3 1125.33   263.11126.448   342.1 1125.64   368.7 1127.52
   374.1 1128.87   378.6 1130.81   389.1 1136.16   396.8 1140.88   405.3 1144.77
   416.7 1148.65   439.4 1154.87   447.9 1156.39   476.3 1168.16   489.6    1173
#Mann= 7 ,-1,0
       0     .06       0      30     .07       0     110     .05       0
     150     .06       0   248.2    .045       0   263.1     .05       0
     280      .1       0
Bank Sta=248.2,263.1
XS Rating Curve= 0 ,0
Exp/Cntr(USF)=0,0
Exp/Cntr=0.3,0.1

Type RM Length L Ch R = 1 ,9899    ,423.4,423.5,407.8
XS GIS Cut Line= 2
2177926.56015771761525.0870459562177497.32454902761187.596452864
#Sta/Elev= 30
       0 1158.74     8.1 1157.05    13.2 1154.74    18.3 1153.42    38.7 1154.03
    44.4 1153.79    48.8  1152.9    53.9 1150.66    72.8 1139.18    78.5  1137.1
    84.4 1136.01     115 1132.37   135.3 1130.58   174.6 1129.03   201.5  1127.1
   215.3 1126.82   257.6  1124.3   263.7 1123.03   274.71124.266   310.5 1125.65
   336.4 1128.97   364.3 1130.61   394.7 1134.24   431.8 1139.89   459.3 1147.62
   477.4 1152.09   488.7 1155.69   497.3 1157.16   504.6 1160.32     546 1175.18
#Mann= 6 ,-1,0
       0     .07       0      50      .1       0      80     .05       0
     240      .1       0   257.6    .045       0   274.7      .1       0
Bank Sta=257.6,274.7
XS Rating Curve= 0 ,0
Exp/Cntr(USF)=0,0
Exp/Cntr=0.3,0.1

Type RM Length L Ch R = 1 ,9476    ,225.1,218.4,209
XS GIS Cut Line= 2
2178145.33373433 761163.585364822177692.41315353760859.880880738
#Sta/Elev= 30
       0 1166.66    25.5 1164.36      40 1156.05    42.9  1155.3    59.2 1155.51
      66 1154.74    68.8 1153.85    78.5 1147.69    91.9  1140.4   112.1 1131.22
     117 1129.69   145.9 1126.78     164  1122.9   178.4 1122.36   242.2 1122.38
   251.8 1122.91   273.2 1123.32   290.4 1124.77   309.6 1128.83   371.6 1131.35
   381.9 1133.44   411.9 1143.28     434  1144.2   452.3  1145.9     483 1151.21
   492.7 1155.85   515.7 1170.83   521.4  1173.9   530.1 1177.78   545.3 1183.19
#Mann= 5 ,-1,0
       0     .06       0      70      .1       0     164    .045       0
   251.8     .08       0     310      .1       0
Bank Sta=164,251.8
XS Rating Curve= 0 ,0
Exp/Cntr(USF)=0,0
Exp/Cntr=0.3,0.1

Type RM Length L Ch R = 1 ,9258    ,249.9,245.1,264.1
XS GIS Cut Line= 5
2178277.65256068761022.419645455 2178235.6467897760945.285198807
2178072.22195642760857.4708597582177897.69139437760771.884937867
2177826.65825018760756.162620476
#Sta/Elev= 30
       0 1170.85    13.8 1165.92    24.2 1160.53      47 1153.86    56.1 1150.22
    69.7 1143.63    74.3 1141.88    78.8 1140.72    96.3 1137.89   114.5 1137.81
   132.6 1135.28   141.7 1134.43   155.3 1129.18   173.2 1126.84   187.9 1122.83
   196.2 1122.41   331.3 1122.42   340.2 1122.82   362.5 1124.48   407.1 1124.75
   433.8  1125.8   438.2 1125.38   442.7 1126.33   451.6  1127.3   458.9 1128.75
   465.1  1130.9   477.5 1137.28   498.1 1145.41   506.2 1147.62   540.5 1154.77
#Mann= 5 ,-1,0
       0     .06       0  147.83      .1       0   187.9    .045       0
   340.2     .07       0  373.35      .1       0
Bank Sta=187.9,340.2
XS Rating Curve= 0 ,0
Exp/Cntr(USF)=0,0
Exp/Cntr=0.3,0.1

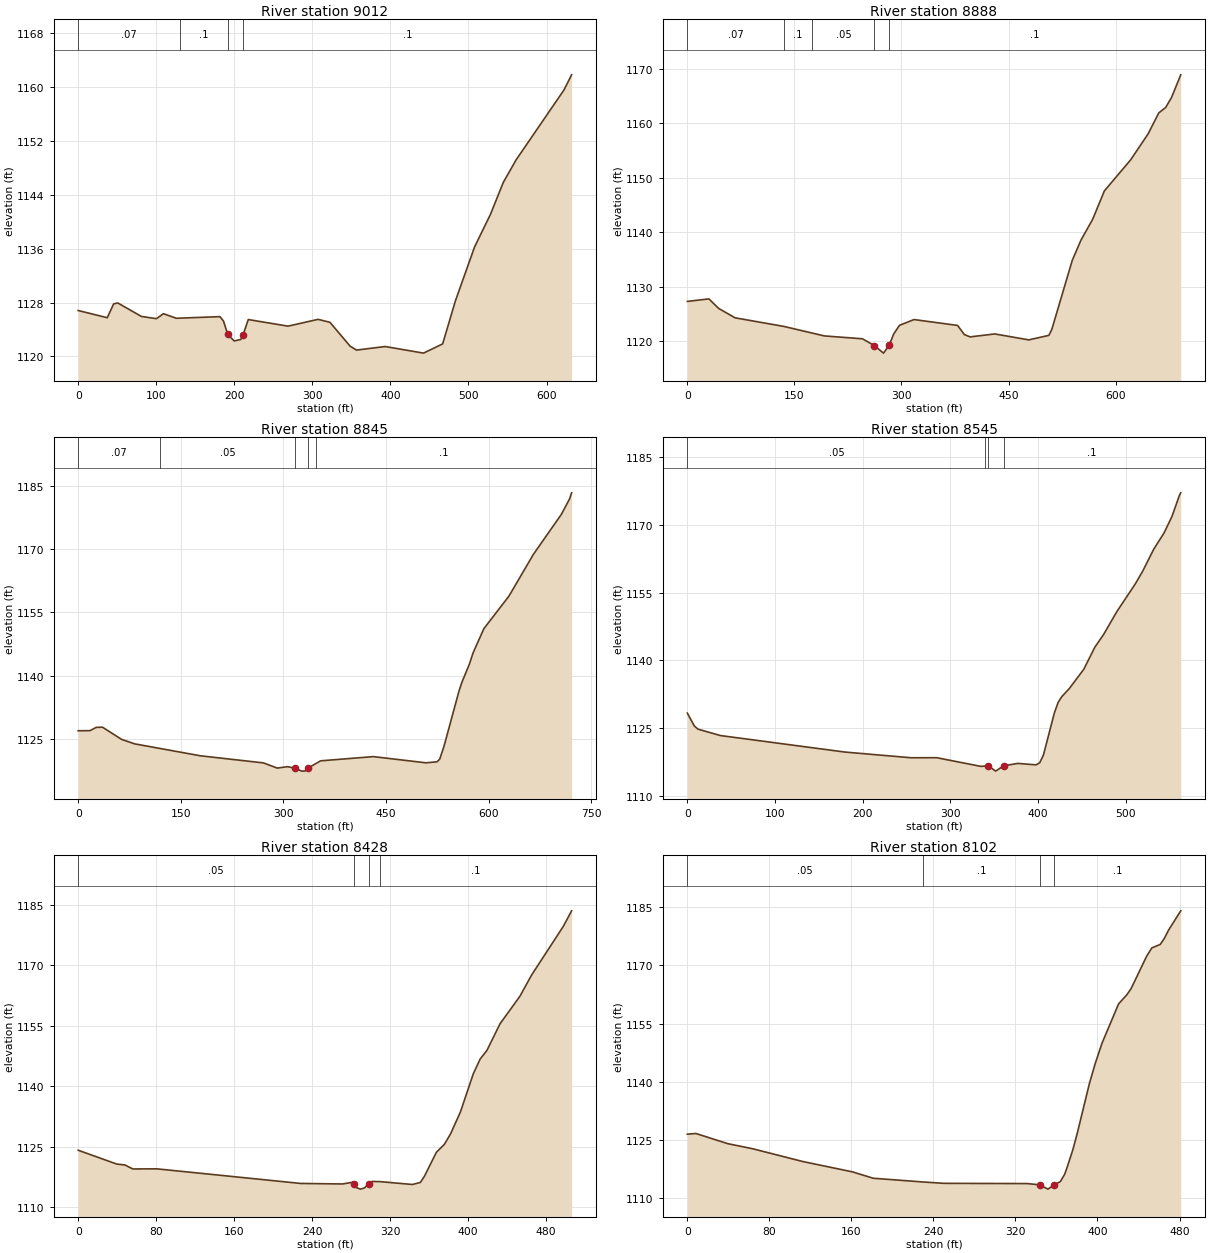
Type RM Length L Ch R = 1 ,9012    ,144.8,124.3,103.1
XS GIS Cut Line= 5
2178393.24045298760749.2485432992178268.00768186760684.764497971
2178185.55602023760640.2440340142178093.75050989760688.954012912
 2177806.5615125760750.216154483
#Sta/Elev= 30
       0 1126.82    37.2 1125.75    45.4  1127.8    50.7 1127.94      81 1125.94
   100.2 1125.61   109.2 1126.35   125.6 1125.67   181.6 1125.91   186.1 1125.26
  191.631123.269   199.8 1122.31   208.3 1122.52  211.33 1123.25   217.9 1125.48
   268.8  1124.5   307.3 1125.51   322.5 1125.07   348.3 1121.54   356.5 1120.95
   393.3 1121.48   442.4  1120.5   466.9 1121.87   483.3 1128.27   507.8 1136.25
   528.2 1141.09   544.6 1145.82     561 1149.16   622.3 1159.52   632.1 1161.77
#Mann= 4 ,-1,0
       0     .07       0     130      .1       0  191.63    .045       0
  211.33      .1       0
Bank Sta=191.63,211.33
XS Rating Curve= 0 ,0
Exp/Cntr(USF)=0,0
Exp/Cntr=0.3,0.1

Type RM Length L Ch R = 1 ,8888    ,44.2,43.2,42
XS GIS Cut Line= 6
2178394.57180188760671.021286831  2178219.407117760575.319061222
2178182.90800541 760569.077330062178159.53262527760589.701420332
2178097.37313828760680.1335217662177791.57848548760745.031087083
#Sta/Elev= 30
       0 1127.27    30.2 1127.73    43.9 1125.98    66.8 1124.26   135.2 1122.68
   191.8 1120.94   245.3 1120.41  261.831119.177   274.8 1117.78   282.7  1119.2
   289.1  1121.3   297.1 1122.87   317.5 1123.94   378.6 1122.86     388 1121.19
   396.1 1120.76   430.7  1121.3   478.3 1120.21   506.5 1121.04   510.6 1122.14
   539.3 1134.83   551.5 1138.53   567.9 1142.36   584.2 1147.54     621 1153.24
   645.6 1158.03   660.4 1161.85   670.1 1162.85   678.3 1164.68   691.2 1168.84
#Mann= 5 ,-1,0
       0     .07       0   135.2      .1       0   175.2     .05       0
  261.83    .045       0   282.7      .1       0
Bank Sta=261.83,282.7
XS Rating Curve= 0 ,0
Exp/Cntr(USF)=0,0
Exp/Cntr=0.3,0.1

Type RM Length L Ch R = 1 ,8845    ,277,299.8,313.2
XS GIS Cut Line= 6
2178406.94196898760651.0032526452178240.88267176760553.977664363
2178170.13132159760542.3215055242178129.98749628760558.610869033
2178068.63698311760664.2740147452177781.33560086 760705.15265098
#Sta/Elev= 30
       0 1126.94    17.1 1126.96    26.4 1127.74    35.5 1127.78    63.4  1124.9
    82.3 1123.84   178.8    1121   270.8 1119.32     291 1118.09     306 1118.43
   317.5 1118.03   326.8 1117.37   331.5 1117.38  335.421118.044   354.3 1119.81
   431.4 1120.81   508.2 1119.34   524.4 1119.57   528.4  1120.2   534.8 1123.32
   556.7 1136.41   560.7 1138.36   571.8 1142.73   577.2  1145.4     593 1151.15
   629.4  1158.8   665.6 1168.81   706.2 1178.22   718.3 1181.91   721.2 1183.33
#Mann= 5 ,-1,0
       0     .07       0     120     .05       0   317.5    .045       0
  335.42     .05       0  347.94      .1       0
Bank Sta=317.5,335.42
XS Rating Curve= 0 ,0
Exp/Cntr(USF)=0,0
Exp/Cntr=0.3,0.1

Type RM Length L Ch R = 1 ,8545    ,117.9,117.3,115.7
XS GIS Cut Line= 3
2178403.79288773760516.8069815142178003.66033825760391.003572239
2177866.66258546 760348.19070306
#Sta/Elev= 30
       0 1128.33       8 1125.48    12.2 1124.78    37.7 1123.37   179.9 1119.71
   255.4 1118.45   284.7 1118.46     335 1116.54   343.4 1116.67   351.8 1115.49
   360.8 1116.66     377  1117.2   397.9 1116.88   402.1 1117.35   406.3 1119.05
   418.9 1128.44   423.1 1130.71   427.3    1132   435.7 1133.74   452.4 1138.06
     465 1142.94   474.8 1145.69   490.1 1150.82   511.1 1156.94   519.5 1159.74
   532.2 1164.64   543.9 1168.22     553 1171.89   561.4 1176.52     563 1177.12
#Mann= 4 ,-1,0
       0     .05       0     340      .1       0   343.4    .045       0
   360.8      .1       0
Bank Sta=343.4,360.8
XS Rating Curve= 0 ,0
Exp/Cntr(USF)=0,0
Exp/Cntr=0.3,0.1

Type RM Length L Ch R = 1 ,8428    ,307.5,325.5,317.4
XS GIS Cut Line= 3
2178386.84779532760366.0549693692177987.95792455760277.503042865
2177891.69948138760261.911486769
#Sta/Elev= 30
       0 1124.19    39.6 1120.76    47.8 1120.55      56 1119.55    80.6 1119.58
   228.1 1115.96   271.2 1115.83   281.4 1116.25  282.51 1115.89   285.5 1114.92
   289.6 1114.55   293.7 1114.85     298 1115.94   301.8 1116.46     310  1116.4
   342.8  1115.7     351 1116.21   355.1 1117.72   367.4 1123.68   375.6 1125.66
   381.9 1128.23     392 1133.64   405.3 1143.17   412.4 1146.84   419.2 1148.92
   432.7 1155.55     453 1162.33   465.1 1167.64   497.5 1179.65   506.1 1183.54
#Mann= 4 ,-1,0
       0     .05       0  282.51    .045       0     298     .05       0
     310      .1       0
Bank Sta=282.51,298
XS Rating Curve= 0 ,0
Exp/Cntr(USF)=0,0
Exp/Cntr=0.3,0.1

Type RM Length L Ch R = 1 ,8102    ,258.6,267.2,263.5
XS GIS Cut Line= 2
2178411.05698202760159.8619918122177936.38164613760080.745618784
#Sta/Elev= 30
       0  1126.5     8.3 1126.68    39.4 1124.06    63.7 1122.75   112.4 1119.47
   161.1 1116.79   181.3 1115.15     230 1114.19   250.3 1113.84   331.6 1113.78
   343.6 1113.45   351.7 1112.35  357.861113.446   363.8  1114.3   367.9 1116.13
   370.1 1117.73     376 1122.52   380.2 1126.65   392.2 1139.62   397.6 1144.53
   404.4 1149.93   420.6 1160.06   428.7 1162.42   432.8 1163.99   447.9 1172.31
     453 1174.47   461.2 1175.37   465.2 1176.92   469.3 1179.04   481.2 1184.02
#Mann= 4 ,-1,0
       0     .05       0     230      .1       0   343.6    .045       0
  357.86      .1       0
Bank Sta=343.6,357.86
XS Rating Curve= 0 ,0
Exp/Cntr(USF)=0,0
Exp/Cntr=0.3,0.1

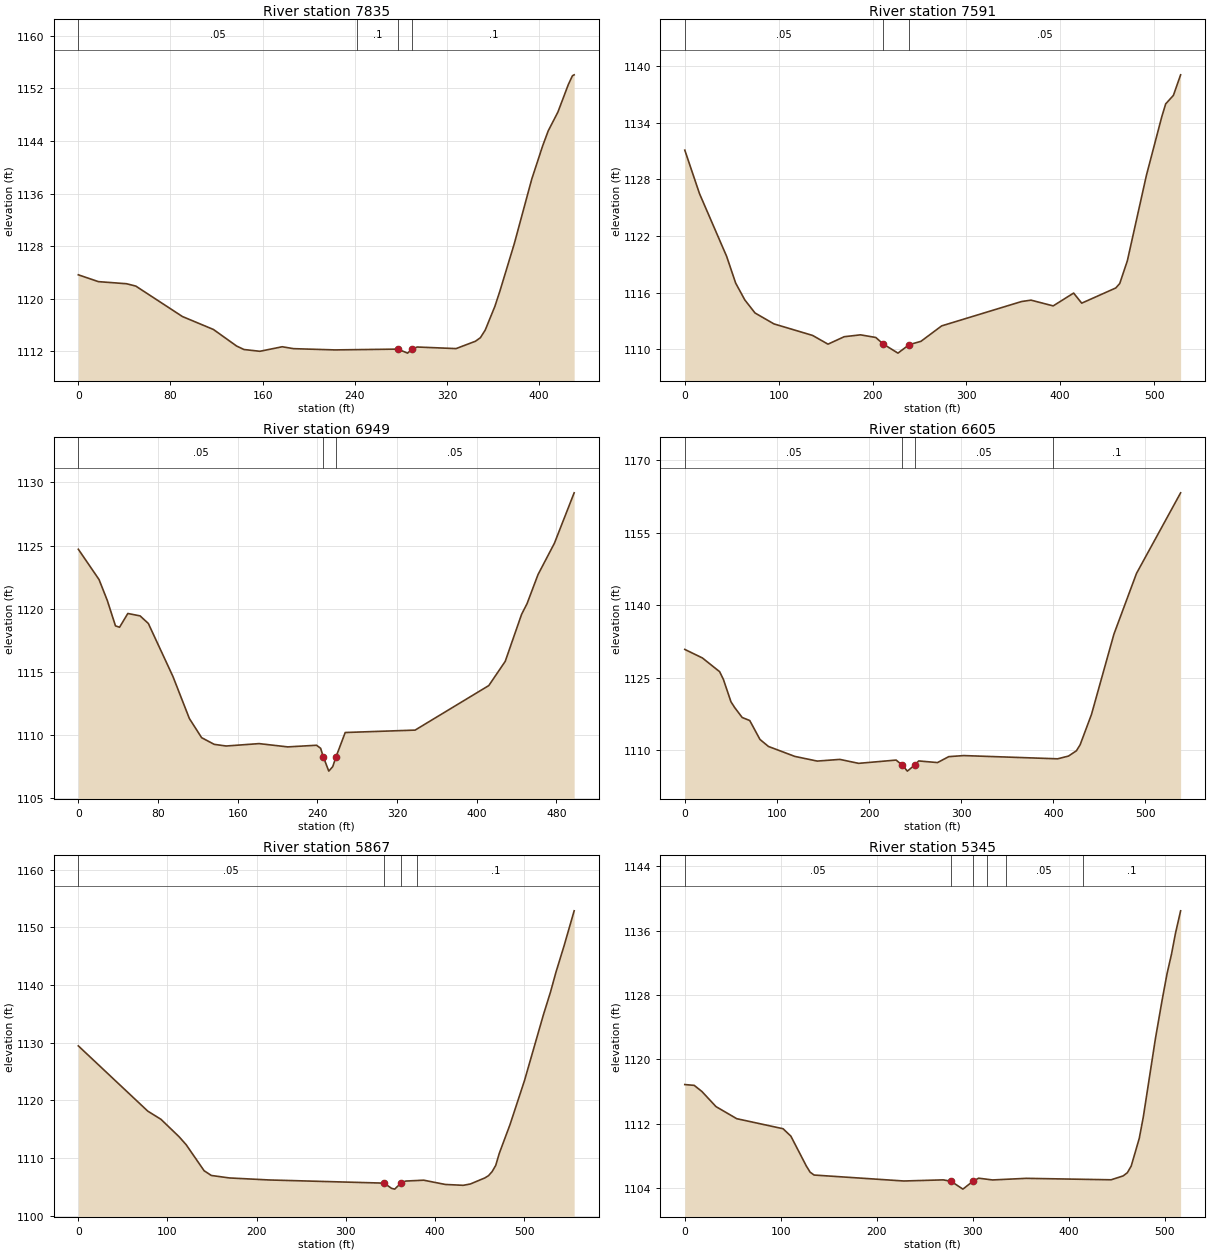
Type RM Length L Ch R = 1 ,7835    ,229.4,244.2,236.5
XS GIS Cut Line= 4
2178401.38398068760043.1333848412178303.54639834760027.118716747
2178219.93666511759967.4592762522178002.81918151759896.167477909
#Sta/Elev= 30
       0 1123.62    17.4 1122.58    41.8 1122.26    49.9  1121.9    90.4 1117.26
   117.3 1115.29   137.4 1112.77   143.8 1112.24   157.6 1111.97     177 1112.66
   186.8 1112.37   222.7 1112.18   277.4  1112.3   285.8 1111.69     290 1112.35
   294.2 1112.62   327.9 1112.38   344.7  1113.5     349 1114.04   353.2  1115.2
   361.6 1118.82   365.8 1121.06   378.4 1128.34   393.6  1138.2   403.1 1143.28
   407.9 1145.55   416.3 1148.41   425.3 1152.58   428.9 1153.94   430.4 1154.08
#Mann= 4 ,-1,0
       0     .05       0  241.85      .1       0   277.4    .045       0
     290      .1       0
Bank Sta=277.4,290
XS Rating Curve= 0 ,0
Exp/Cntr(USF)=0,0
Exp/Cntr=0.3,0.1

Type RM Length L Ch R = 1 ,7591    ,620.3,641.4,607.5
XS GIS Cut Line= 3
 2178477.2501608759939.8674478032178182.66220607759742.664244345
2178012.57801438759778.528960935
#Sta/Elev= 30
       0  1131.1    15.7 1126.48    44.6 1119.83    54.2    1117    63.9 1115.22
    74.8 1113.83      95 1112.67   136.1 1111.45   152.6 1110.52   169.8 1111.31
   187.2 1111.51   203.5 1111.23   211.31110.544   227.1 1109.57   239.1 1110.47
   251.6 1110.82   273.7 1112.46   358.7 1115.04   368.9 1115.19   392.5 1114.58
   414.3 1115.94   422.9 1114.87   459.2 1116.48   463.4 1116.95   471.5 1119.35
   491.9 1128.45   508.3 1134.67   512.4 1136.01   520.6 1136.91   528.3 1139.09
#Mann= 3 ,-1,0
       0     .05       0   211.3    .045       0   239.1     .05       0
Bank Sta=211.3,239.1
XS Rating Curve= 0 ,0
Exp/Cntr(USF)=0,0
Exp/Cntr=0.3,0.1

Type RM Length L Ch R = 1 ,6949    ,336.8,344.7,330.6
XS GIS Cut Line= 2
2178560.39444424759482.2052642432178076.91592653759363.098725033
#Sta/Elev= 30
       0 1124.71    20.8 1122.31    29.1 1120.65    37.3 1118.64    41.4 1118.53
    49.7 1119.62      62 1119.43    70.3 1118.83      95 1114.63   111.5  1111.3
   123.8 1109.78   136.5 1109.25   148.5 1109.12   181.5 1109.31   210.3 1109.05
   239.2 1109.18   243.3 1108.94  246.131108.238   251.5 1107.13   255.5 1107.49
   258.8 1108.27     268 1110.19   338.2 1110.38   412.2 1113.91   428.7 1115.83
   445.1 1119.55   450.6  1120.4   461.6  1122.7   478.1 1125.19   497.9 1129.18
#Mann= 3 ,-1,0
       0     .05       0  246.13    .045       0   258.8     .05       0
Bank Sta=246.13,258.8
XS Rating Curve= 0 ,0
Exp/Cntr(USF)=0,0
Exp/Cntr=0.3,0.1

Type RM Length L Ch R = 1 ,6605    ,730.8,738,727
XS GIS Cut Line= 2
2178669.31423997759240.8578032132178141.17077005759137.423177057
#Sta/Elev= 30
       0 1130.85    19.1 1129.08    37.8 1126.24    41.9 1124.64    50.1 1120.01
    54.1 1118.82    62.3 1116.75    70.5 1116.12    81.6  1112.2    90.8 1110.75
   119.4 1108.69   143.8 1107.72   168.3 1108.07   188.7 1107.25   229.4 1107.93
  236.171106.862   241.6 1105.64   249.5 1106.89   253.9 1107.75   274.3 1107.41
   286.5 1108.64   302.8 1108.86   404.7 1108.19   416.5 1108.76   425.1 1109.86
   429.1 1111.09   441.4 1117.36   465.8 1134.01   490.3 1146.59   538.2 1163.28
#Mann= 4 ,-1,0
       0     .05       0  236.17    .045       0   249.5     .05       0
     400      .1       0
Bank Sta=236.17,249.5
XS Rating Curve= 0 ,0
Exp/Cntr(USF)=0,0
Exp/Cntr=0.3,0.1

Type RM Length L Ch R = 1 ,5867    ,510.4,521.6,514.9
XS GIS Cut Line= 2
2178752.01347325758937.0988685232178201.00092489758861.566811333
#Sta/Elev= 30
       0 1129.45    77.9 1118.13    92.7 1116.71   112.9 1113.71     121  1112.3
   141.1 1107.79   149.2 1106.97   169.4 1106.54   213.8 1106.19     343 1105.64
   351.3 1104.74   354.9  1104.6     362 1105.67   367.2    1106   387.4 1106.15
   411.6 1105.41   431.8 1105.26   439.9  1105.5   456.1 1106.55   460.1 1106.93
   464.1 1107.62   468.2 1108.71   472.2  1110.8   484.3 1115.82   500.5 1123.44
   521.7 1134.84   529.6 1138.76   535.9 1142.29   544.9 1146.82   556.2 1152.88
#Mann= 4 ,-1,0
       0     .05       0     343    .045       0     362     .05       0
     380      .1       0
Bank Sta=343,362
XS Rating Curve= 0 ,0
Exp/Cntr(USF)=0,0
Exp/Cntr=0.3,0.1

Type RM Length L Ch R = 1 ,5345    ,179.7,191.4,193.2
XS GIS Cut Line= 4
2178785.88720172758675.6409149372178612.57456269758654.879505054
2178466.34202351758622.3833852362178283.10001453758564.612505559
#Sta/Elev= 30
       0 1116.87     9.8 1116.77    17.8 1116.01    32.5 1114.13    54.1 1112.63
   102.4 1111.38   110.5 1110.46   126.6 1106.75   130.6 1105.98   134.7 1105.63
   228.2 1104.89   269.2 1105.03   277.4 1104.85   289.7 1103.88   300.4 1104.88
   306.1 1105.24   320.5 1105.02   355.7 1105.22   444.1 1105.04   456.6 1105.52
     461 1105.92     465 1106.74   473.4 1110.18   477.6 1112.82   490.2 1122.54
   497.3 1127.41   502.4 1130.67     507 1133.07   511.2 1135.69   516.5 1138.45
#Mann= 6 ,-1,0
       0     .05       0   277.4    .045       0   300.4     .05       0
  314.55      .1       0  334.35     .05       0  414.35      .1       0
Bank Sta=277.4,300.4
XS Rating Curve= 0 ,0
Exp/Cntr(USF)=0,0
Exp/Cntr=0.3,0.1

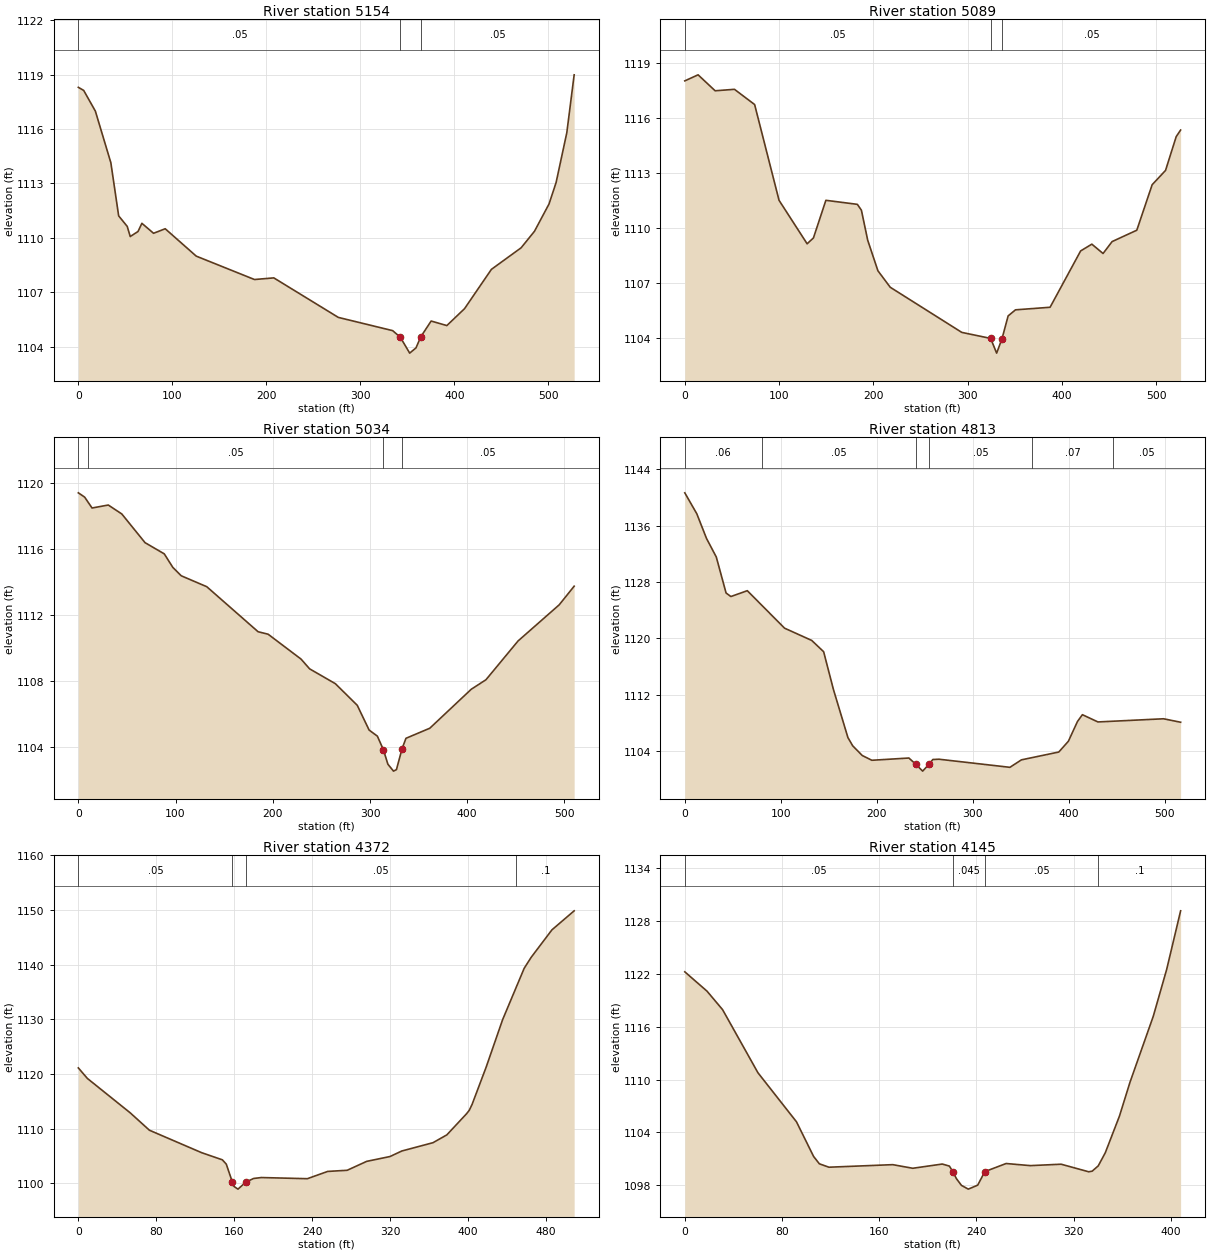
Type RM Length L Ch R = 1 ,5154    ,62.8,64.9,66.4
XS GIS Cut Line= 3
2178833.72871145758618.7727052562178565.63572295758551.072455635
2178362.53497409758403.937246458
#Sta/Elev= 30
       0  1118.3     5.7 1118.13    18.1 1116.99    34.6 1114.14    42.9 1111.21
      52 1110.63    55.2 1110.07    63.5 1110.35    67.6  1110.8      80 1110.25
    92.4  1110.5   125.4 1108.99   187.3  1107.7   207.9 1107.79   276.5 1105.61
   334.3 1104.88   342.5 1104.51   352.4 1103.64   359.1 1103.93   364.2 1104.54
   375.2 1105.41   391.9 1105.16   410.7 1106.09   439.3 1108.26   470.9 1109.45
   485.1 1110.36   500.6 1111.87   508.1 1113.05   519.5  1115.8   527.3 1118.99
#Mann= 3 ,-1,0
       0     .05       0   342.5    .045       0   364.2     .05       0
Bank Sta=342.5,364.2
XS Rating Curve= 0 ,0
Exp/Cntr(USF)=0,0
Exp/Cntr=0.3,0.1

Type RM Length L Ch R = 1 ,5089    ,56,55.1,54.5
XS GIS Cut Line= 6
2178853.32977377758605.6226121062178771.18680423758574.029162283
2178680.91980473758534.3116825042178593.24711123758496.050541315
2178498.58046575758426.8939531062178404.70278628758342.042973581
#Sta/Elev= 30
       0 1118.04    14.1 1118.37    32.2  1117.5    52.7 1117.58    74.1 1116.75
     100 1111.53   129.8 1109.16   136.5 1109.48   149.7 1111.53   183.1 1111.31
   187.4 1110.99   194.1 1109.35   204.9 1107.69     218 1106.79   293.9 1104.33
  324.521104.002   330.9  1103.2   336.6 1103.99   343.1 1105.23   350.9 1105.56
   387.6  1105.7     420 1108.77   431.9 1109.14   443.8 1108.63   453.4 1109.28
   479.6  1109.9   495.9 1112.38   510.1 1113.16   521.4    1115   526.1 1115.36
#Mann= 3 ,-1,0
       0     .05       0  324.52    .045       0   336.6     .05       0
Bank Sta=324.52,336.6
XS Rating Curve= 0 ,0
Exp/Cntr(USF)=0,0
Exp/Cntr=0.3,0.1

Type RM Length L Ch R = 1 ,5034    ,215.2,220.7,219.1
XS GIS Cut Line= 5
 2178881.0772462 758568.848439722178743.87140697758508.369550058
 2178631.9403276758456.0146903512178547.99201807758396.438470685
2178448.69831862758307.074141185
#Sta/Elev= 30
       0 1119.42     6.5 1119.16    14.1  1118.5    30.8 1118.68    44.7 1118.14
    68.6  1116.4    88.4 1115.72    97.2  1114.9   105.9 1114.39   132.1 1113.73
   184.9    1111   195.2 1110.85   229.1 1109.34   237.9 1108.75   264.4 1107.85
   286.9 1106.54   299.1 1105.04   307.6 1104.67   313.81103.844   318.4 1102.97
   324.2 1102.55   327.2 1102.64     3331103.908     337 1104.54   361.5 1105.15
   404.1 1107.51   419.3 1108.09   452.3 1110.44   494.6 1112.63     510 1113.76
#Mann= 4 ,-1,0
       0     .06       0      10     .05       0   313.8    .045       0
     333     .05       0
Bank Sta=313.8,333
XS Rating Curve= 0 ,0
Exp/Cntr(USF)=0,0
Exp/Cntr=0.3,0.1

Type RM Length L Ch R = 1 ,4813    ,442.1,440.6,425.7
XS GIS Cut Line= 4
2178933.97714813758442.7566872992178806.52737882758342.831939581
2178610.64798992  758196.59940042178507.25573878758158.941826729
#Sta/Elev= 30
       0 1140.66    12.5 1137.69    22.6 1134.19    32.8 1131.55      43 1126.44
      48 1125.94    65.1 1126.77   103.9 1121.45   132.2 1119.71   144.6 1118.11
   154.8 1112.75   169.9 1105.92   174.9 1104.75   184.8 1103.38   194.8  1102.7
   233.4 1103.02  240.651102.124   247.7 1101.16   254.7 1102.18   258.3 1102.81
   264.7 1102.85   338.6  1101.7   350.6 1102.76   389.5 1103.87   399.5  1105.4
     409 1108.21   414.1 1109.17   430.3 1108.14   498.6 1108.59   516.4  1108.1
#Mann= 6 ,-1,0
       0     .06       0      80     .05       0  240.65    .045       0
   254.7     .05       0  361.95     .07       0   446.4     .05       0
Bank Sta=240.65,254.7
XS Rating Curve= 0 ,0
Exp/Cntr(USF)=0,0
Exp/Cntr=0.3,0.1

Type RM Length L Ch R = 1 ,4372    ,198.3,227.1,231.6
XS GIS Cut Line= 4
2178904.64594777758137.3643108212178789.45738683758084.863402091
2178546.54273449758074.6766586062178431.35417355757996.317093336
#Sta/Elev= 30
       0 1121.11     9.3 1119.18    53.3 1112.88      73  1109.7   126.6 1105.59
   147.9 1104.28   151.9 1103.49  158.121100.211   159.9  1099.4   163.9 1098.92
   171.9 1100.19   179.9 1100.87   187.9 1101.04   235.1 1100.83     256 1102.16
     276 1102.37     296    1104     320 1104.89   332.1  1105.9   364.1 1107.42
   378.3 1108.85   398.4 1112.69   401.3 1113.34   404.2 1114.42   418.6 1121.22
   435.5 1129.91   457.7 1139.34   464.8 1141.33   486.2 1146.38     509 1149.86
#Mann= 4 ,-1,0
       0     .05       0  158.12    .045       0   171.9     .05       0
  449.72      .1       0
Bank Sta=158.12,171.9
XS Rating Curve= 0 ,0
Exp/Cntr(USF)=0,0
Exp/Cntr=0.3,0.1

Type RM Length L Ch R = 1 ,4145    ,286.3,304.7,297.2
XS GIS Cut Line= 2
2178909.47759494758105.722815599 2178629.6498965757808.744387261
#Sta/Elev= 30
       0 1122.25    18.3 1120.05    31.1 1117.95    60.2 1110.78    91.9 1105.21
     106 1101.27   110.7 1100.44   118.6 1100.05   171.1 1100.34   187.6 1099.93
   211.9 1100.41   217.7 1100.18   220.6 1099.54   223.5 1098.75   227.7 1097.98
   233.3 1097.56     241 1098.01   246.9 1099.55   264.4 1100.47   284.3 1100.23
   309.7 1100.39   332.4 1099.53   335.2  1099.6   340.2  1100.2     346 1101.69
   357.7 1105.87   366.3 1109.69   385.5  1117.2   396.5 1122.51     408 1129.18
#Mann= 4 ,-1,0
       0     .05       0   220.6    .045       0   246.9     .05       0
     340      .1       0
Bank Sta=220.6,246.9
XS Rating Curve= 0 ,0
Exp/Cntr(USF)=0,0
Exp/Cntr=0.3,0.1

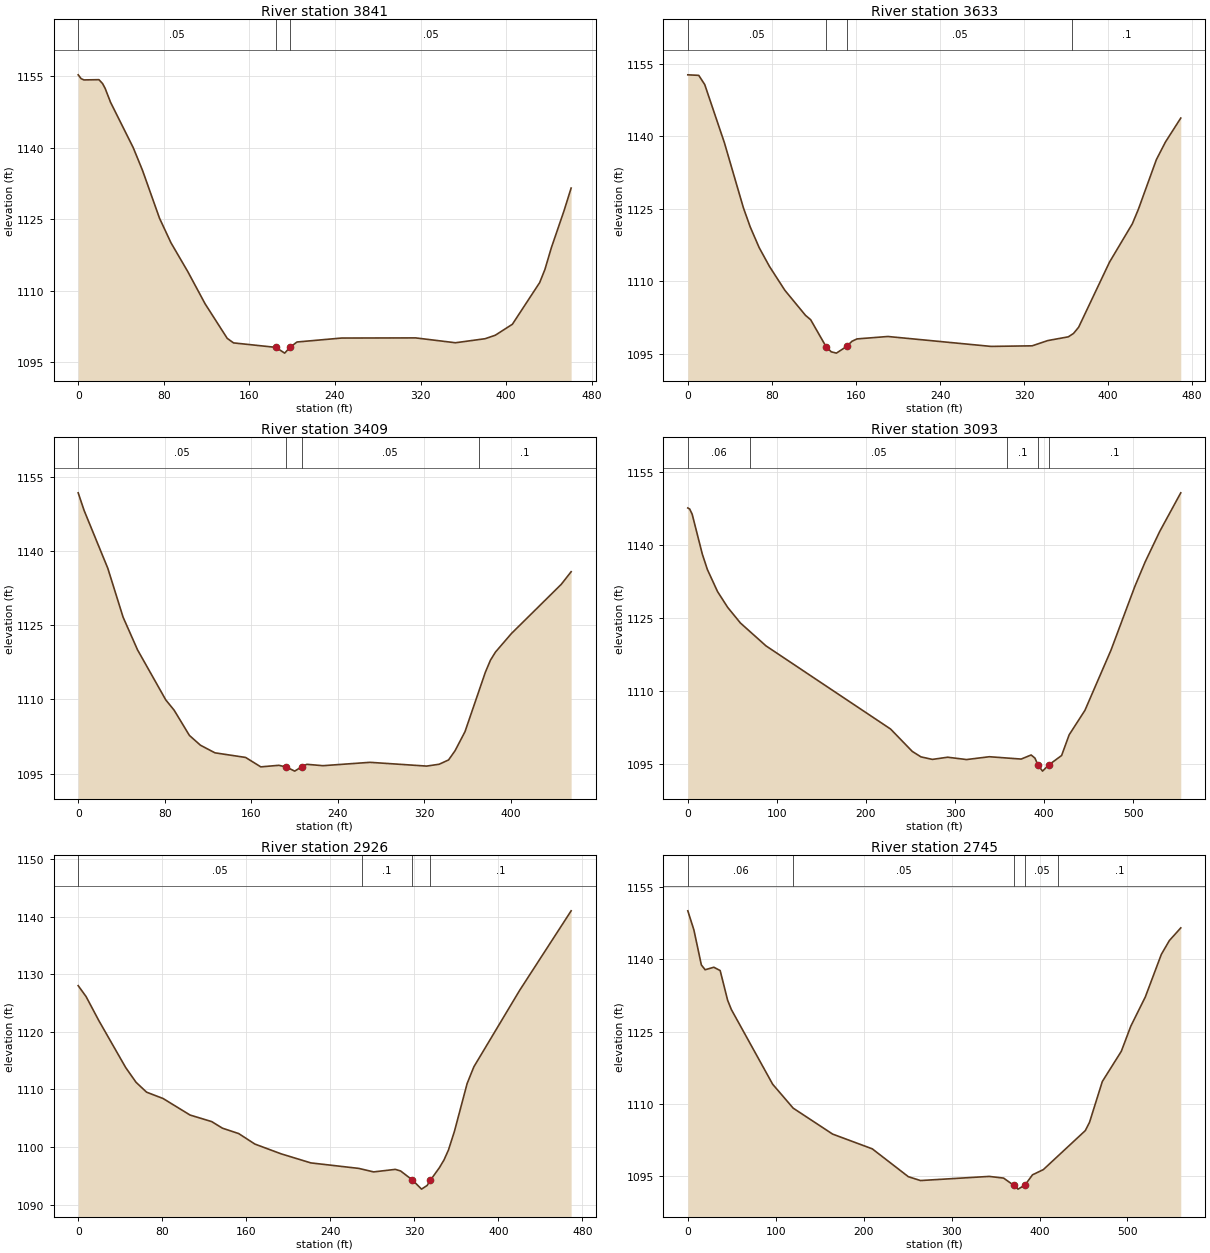
Type RM Length L Ch R = 1 ,3841    ,206.9,207.5,204.2
XS GIS Cut Line= 3
2179052.53341764757984.6665713822179005.79912423757950.431243385
2178702.88873385757685.044683998
#Sta/Elev= 30
       0 1155.34     2.8 1154.53     5.4 1154.27    19.4 1154.32    22.8  1153.5
    25.2 1152.49    30.2 1149.59    51.4 1140.05    60.1 1135.27      76  1125.2
    86.7 1120.04   102.5 1113.95   118.6 1107.21   139.3 1099.94   145.2 1098.99
   184.7 1098.05     193 1096.84  197.921098.062   204.5 1099.18   246.2 1100.01
   315.4 1100.04   352.6 1099.02   380.3 1099.87   389.8  1100.6   405.8 1102.91
   431.3 1111.67   436.2 1114.43   442.2 1118.99     454 1126.73   460.7 1131.54
#Mann= 3 ,-1,0
       0     .05       0   184.7    .045       0  197.92     .05       0
Bank Sta=184.7,197.92
XS Rating Curve= 0 ,0
Exp/Cntr(USF)=0,0
Exp/Cntr=0.3,0.1

Type RM Length L Ch R = 1 ,3633    ,222,224.1,220.2
XS GIS Cut Line= 3
 2179163.8232866757816.1958251412179121.97877099757779.219132368
2178784.85393552757540.191584015
#Sta/Elev= 30
       0 1152.67    10.4 1152.56    16.1 1150.66    34.8 1138.64    52.9 1125.17
    59.4 1121.21    67.9 1116.94    77.7 1113.05    92.4  1108.1     112 1102.93
   116.9 1102.03   131.6 1096.45   136.5 1095.39   141.4 1095.12   151.2 1096.51
   156.2 1097.57     161 1098.06   190.4 1098.56   288.5 1096.51   327.7 1096.63
   342.6 1097.72   362.1 1098.49     367 1099.18   371.9 1100.47   401.3 1113.94
     423 1121.86   428.7 1124.83   445.9 1135.14   454.5 1138.77   469.1 1143.73
#Mann= 4 ,-1,0
       0     .05       0   131.6    .045       0   151.2     .05       0
  365.84      .1       0
Bank Sta=131.6,151.2
XS Rating Curve= 0 ,0
Exp/Cntr(USF)=0,0
Exp/Cntr=0.3,0.1

Type RM Length L Ch R = 1 ,3409    ,312.8,316.1,308.8
XS GIS Cut Line= 2
2179287.40819395757637.5876498562178900.89969903757396.335973841
#Sta/Elev= 30
       0  1151.8     5.5 1148.22    27.4 1136.52    41.5 1126.65    54.9 1120.02
      81  1109.9    88.7 1107.83   102.8 1102.73     113 1100.75   126.4 1099.21
   154.7 1098.28   168.8 1096.37   185.5 1096.69   192.4 1096.33   200.1 1095.51
   206.6 1096.39   211.3 1096.89   226.2 1096.61   269.7 1097.29     322 1096.53
   333.6  1096.9   342.3 1097.77   348.3 1099.63   357.5 1103.49   376.3  1115.5
     381 1117.94   385.7  1119.6   400.4 1123.34   446.5  1133.3   455.6 1135.84
#Mann= 4 ,-1,0
       0     .05       0   192.4    .045       0   206.6     .05       0
     370      .1       0
Bank Sta=192.4,206.6
XS Rating Curve= 0 ,0
Exp/Cntr(USF)=0,0
Exp/Cntr=0.3,0.1

Type RM Length L Ch R = 1 ,3093    ,162.8,166.9,169.8
XS GIS Cut Line= 3
2179417.12790379 757523.158410842179244.61763809757388.760878258
2178930.68907318757272.416745576
#Sta/Elev= 30
       0  1147.7     2.1 1147.48     4.9 1146.41    16.3  1138.2      22 1135.03
    33.4  1130.5    44.8 1127.25    59.1 1124.04    87.8 1119.34   227.7 1102.24
     252 1097.65   261.8 1096.52   274.6    1096   291.7 1096.45     313 1095.97
   338.6 1096.55   374.3 1096.07   385.5 1096.91   389.8 1096.26     393 1094.91
   398.3 1093.59   405.4 1094.88   419.7  1096.8   428.2 1101.06   445.9 1106.09
   475.1 1118.44   501.9 1131.55   513.5  1136.6   529.9 1142.88   553.5 1150.81
#Mann= 5 ,-1,0
       0     .06       0      70     .05       0  358.68      .1       0
     393    .045       0   405.4      .1       0
Bank Sta=393,405.4
XS Rating Curve= 0 ,0
Exp/Cntr(USF)=0,0
Exp/Cntr=0.3,0.1

Type RM Length L Ch R = 1 ,2926    ,183.4,180.9,173.7
XS GIS Cut Line= 3
2179438.99507698757409.9018521812179110.45101767757144.380171331
2179071.13114745757119.104035661
#Sta/Elev= 30
       0 1128.02     7.5 1126.13    19.6 1121.97    45.2 1113.81    55.1 1111.24
    65.1 1109.53    80.8 1108.43   106.5 1105.56   127.1 1104.42   137.3 1103.28
   152.8 1102.34   168.2 1100.52   193.1 1098.83   221.5 1097.25     267  1096.3
   281.2 1095.69   301.9 1096.13   306.9 1095.85   318.2 1094.27   326.8  1092.7
   332.1 1093.33   335.3 1094.26   343.8 1096.42   348.2 1097.77   352.4 1099.48
   358.1 1102.72   370.2 1111.03   376.6 1113.93   420.2 1127.21   469.2 1141.01
#Mann= 4 ,-1,0
       0     .05       0     270      .1       0   318.2    .045       0
   335.3      .1       0
Bank Sta=318.2,335.3
XS Rating Curve= 0 ,0
Exp/Cntr(USF)=0,0
Exp/Cntr=0.3,0.1

Type RM Length L Ch R = 1 ,2745    ,171.8,171.7,170.7
XS GIS Cut Line= 4
2179670.65850774 757192.769592922179482.24166867757123.216659676
2179262.54517465757071.6628191572179144.76317861757007.590550773
#Sta/Elev= 30
       0 1150.07     6.9 1146.12    15.4 1138.84    19.7 1137.84    29.6 1138.36
    36.8 1137.67    45.3  1131.5    49.5 1129.59    96.5 1114.08   119.8 1109.12
   164.7 1103.73   209.8 1100.67   250.8 1094.89   264.6 1094.09   342.7 1094.95
   359.1  1094.6   370.6 1093.11   375.5 1092.31   383.4 1093.15     392 1095.28
   404.3 1096.36     452 1104.45   456.8 1106.16   471.4 1114.65     493 1120.92
   503.8 1126.14   520.3  1132.2   538.5 1141.03   547.6 1143.89   560.6 1146.53
#Mann= 5 ,-1,0
       0     .06       0     120     .05       0   370.6    .045       0
   383.4     .05       0  420.84      .1       0
Bank Sta=370.6,383.4
XS Rating Curve= 0 ,0
Exp/Cntr(USF)=0,0
Exp/Cntr=0.3,0.1