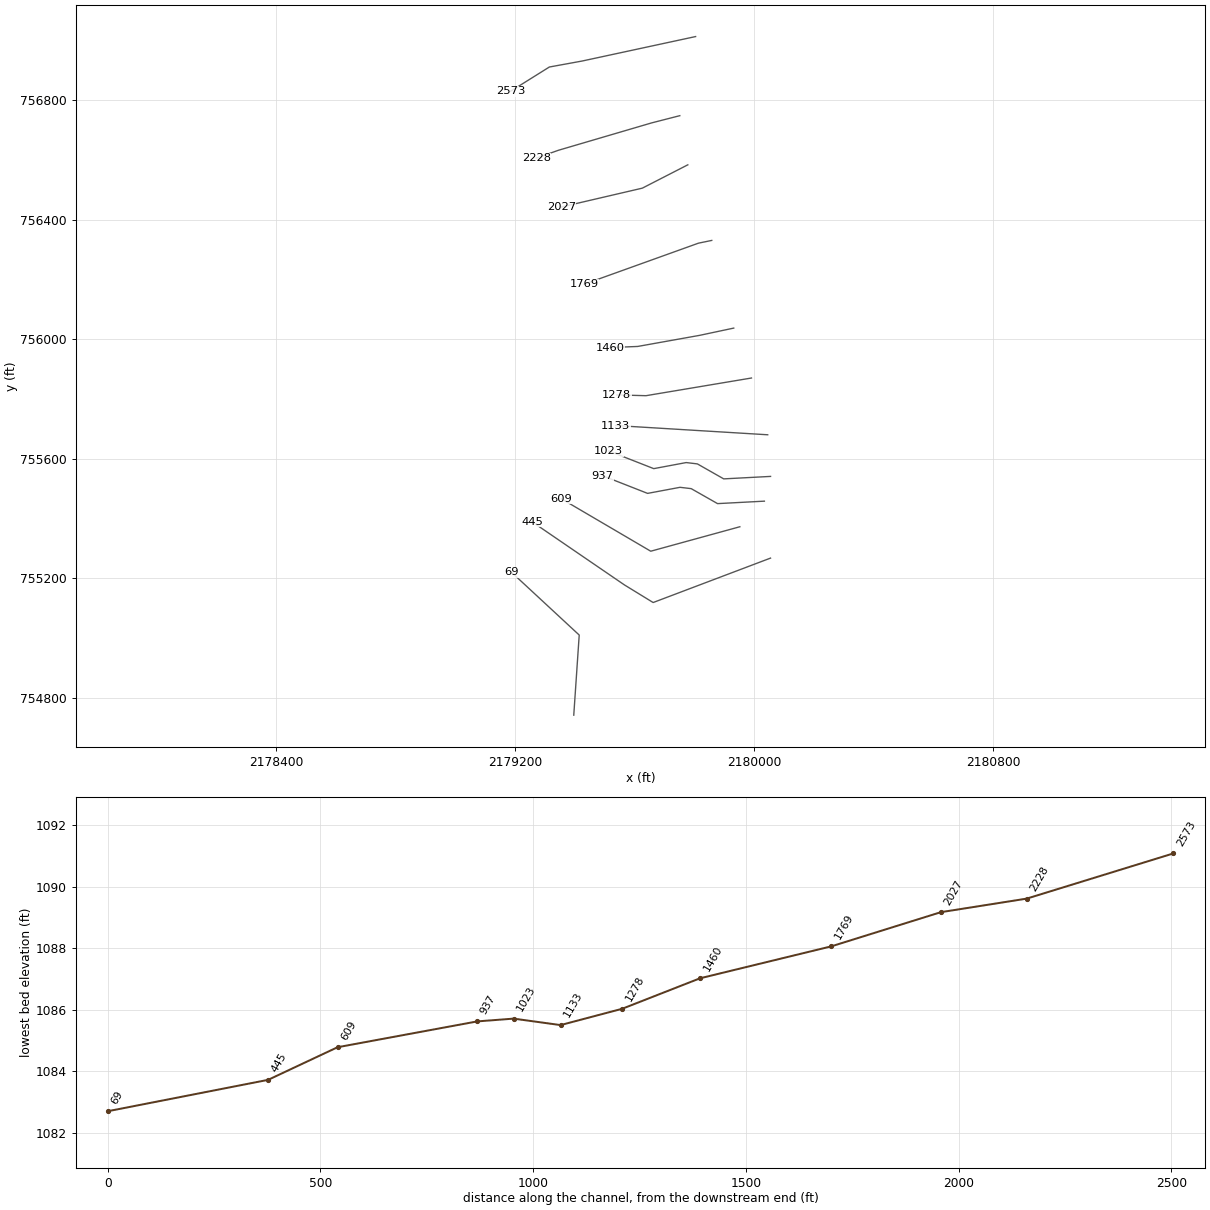
HEC-RAS study HACKCKT2.prj: HACKCKT2

--- HACKCKT2.g01 (geometry) --- (continued)

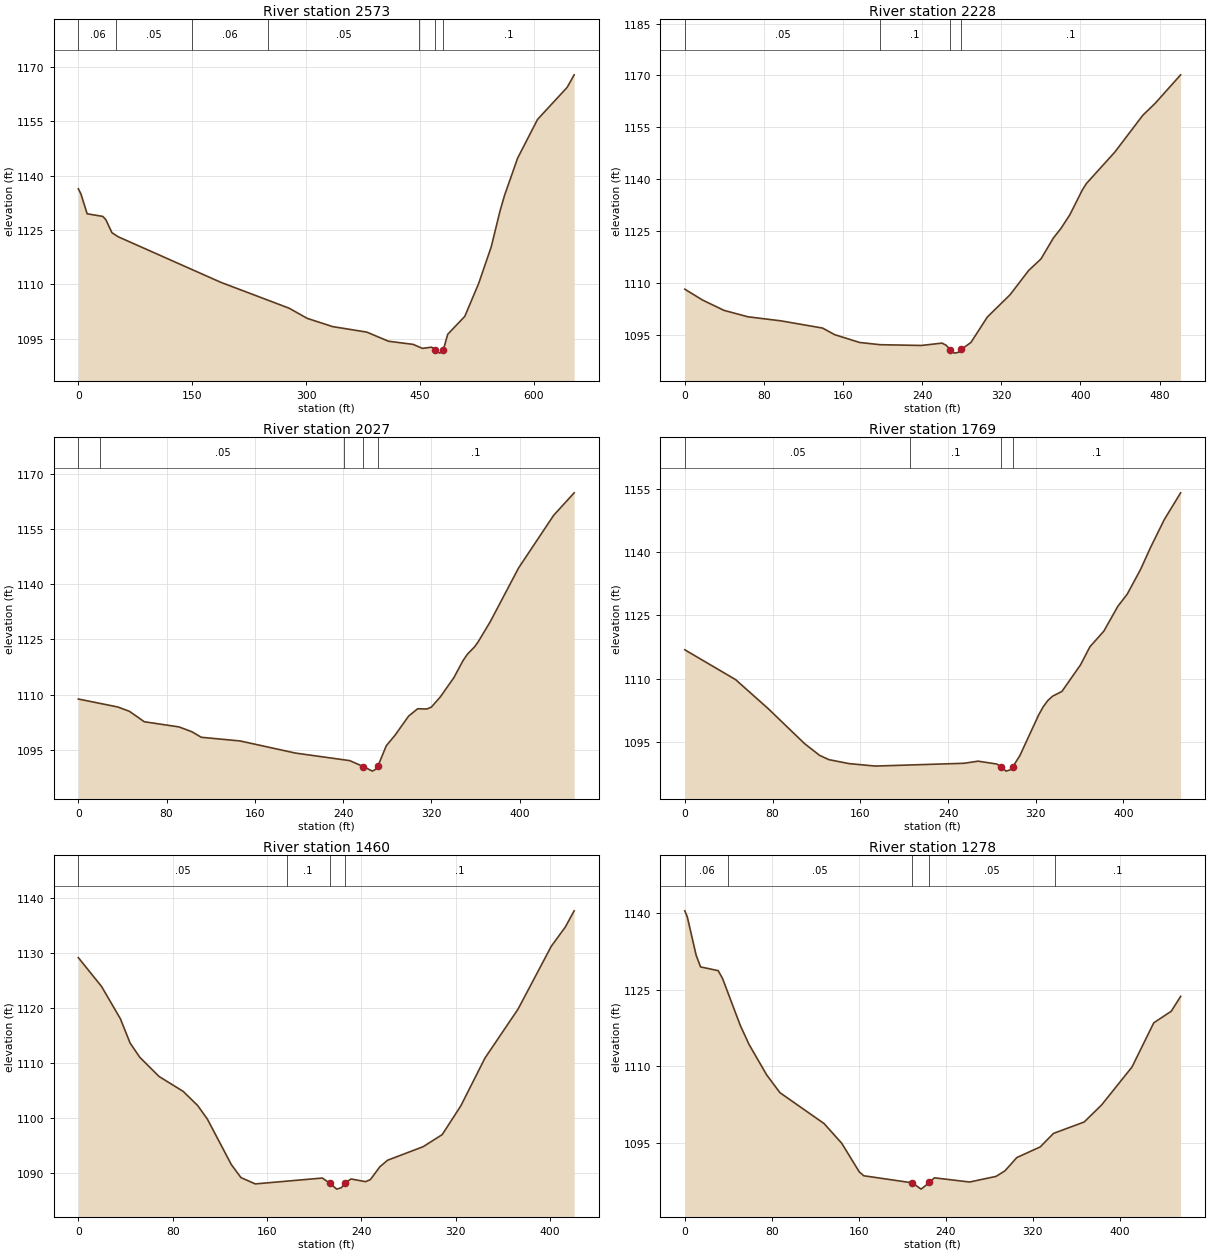
Type RM Length L Ch R = 1 ,2573    ,341.6,345,343.6
XS GIS Cut Line= 4
2179803.51309101757013.4066845852179423.61761437756931.486263507
  2179313.914223756911.4610412722179184.36777618 756830.48142775
#Sta/Elev= 30
       0 1136.38     3.4 1134.98    11.6 1129.49    32.1 1128.77    36.2 1127.88
    44.3 1124.27    52.5 1123.15   187.6  1110.6   277.6 1103.46   301.4 1100.66
   334.9 1098.39   379.9 1096.87   408.4 1094.36   440.9 1093.49   453.1 1092.39
   465.3 1092.72  469.941091.865   476.1 1091.08   479.6 1091.87   481.6  1092.7
   486.4 1096.27   508.9 1101.22   527.1 1110.25   543.7 1120.36   555.3 1130.29
   561.3  1134.6   578.5 1144.85   604.7  1155.5   643.7 1164.34   652.9 1167.79
#Mann= 7 ,-1,0
       0     .06       0      50     .05       0     150     .06       0
     250     .05       0  448.63      .1       0  469.94    .045       0
   479.6      .1       0
Bank Sta=469.94,479.6
XS Rating Curve= 0 ,0
Exp/Cntr(USF)=0,0
Exp/Cntr=0.3,0.1

Type RM Length L Ch R = 1 ,2228    ,201.7,201.7,200.4
XS GIS Cut Line= 4
2179750.60666802 756748.586684052179656.32424381756724.411173094
2179344.29017149756632.7821201092179270.07416128756606.423297309
#Sta/Elev= 30
       0 1108.12    17.9 1104.98    39.7 1101.98      64 1100.12    96.8 1098.97
   139.2 1096.87   151.6 1094.95   176.7  1092.7   197.5 1092.05   239.2 1091.83
   260.1 1092.51   264.2  1091.9   268.4  1090.6   272.6 1089.61   276.8 1089.85
  279.461090.676   289.3  1092.7   305.9 1100.07   328.9 1106.52   347.6 1113.52
   360.1 1116.87   372.6 1122.91   380.4 1125.75   389.3 1129.66   401.8 1136.77
     406 1138.69   434.9 1147.85     463 1158.44   475.6 1161.93   501.3 1170.17
#Mann= 4 ,-1,0
       0     .05       0  197.33      .1       0   268.4    .045       0
  279.46      .1       0
Bank Sta=268.4,279.46
XS Rating Curve= 0 ,0
Exp/Cntr(USF)=0,0
Exp/Cntr=0.3,0.1

Type RM Length L Ch R = 1 ,2027    ,255.4,257.3,257.8
XS GIS Cut Line= 3
2179777.40430183756584.0838346262179625.15119348756505.986590916
2179353.97872586756442.836838182
#Sta/Elev= 30
       0 1108.78    35.8 1106.61    46.3 1105.44    59.8  1102.6    91.3 1101.19
   102.8  1099.9   111.5 1098.37   146.6 1097.38   196.8 1094.08     246 1092.03
   258.4 1090.41   266.6 1089.17   270.7 1089.87  271.471090.435   279.2 1096.08
   287.1 1098.93   299.4 1104.13   307.6 1106.13   315.9 1106.06     320 1106.57
   328.2 1109.36   340.5 1114.62   348.7  1119.2   352.8 1120.99   359.2 1122.96
   362.5 1124.34   373.4 1129.78   399.1 1144.41   430.9 1158.73   449.5 1164.85
#Mann= 5 ,-1,0
       0     .06       0      20     .05       0  241.11      .1       0
   258.4    .045       0  271.47      .1       0
Bank Sta=258.4,271.47
XS Rating Curve= 0 ,0
Exp/Cntr(USF)=0,0
Exp/Cntr=0.3,0.1

Type RM Length L Ch R = 1 ,1769    ,309.5,309,305.1
XS GIS Cut Line= 3
2179857.52215281756331.0253933852179812.94380446756321.789808799
2179430.33059672756184.346229321
#Sta/Elev= 30
       0 1116.84    46.3 1109.77    76.1 1102.87   109.1 1094.61   122.8 1091.82
   131.3 1090.79   149.8 1089.84   173.8 1089.26   254.6 1089.92   267.4 1090.42
   284.4 1089.75   288.6 1089.08   292.9 1088.06   297.1  1088.4  299.191089.123
   305.6 1091.78   322.6 1101.36   326.9 1103.36   331.1 1104.83   335.4 1105.84
   343.9 1106.97   360.9  1113.3   369.4 1117.56   382.1 1121.27   394.9 1127.17
   403.4 1130.03   415.6 1135.91   424.6 1141.07   437.1 1147.67   452.1 1154.07
#Mann= 4 ,-1,0
       0     .05       0  205.52      .1       0   288.6    .045       0
  299.19      .1       0
Bank Sta=288.6,299.19
XS Rating Curve= 0 ,0
Exp/Cntr(USF)=0,0
Exp/Cntr=0.3,0.1

Type RM Length L Ch R = 1 ,1460    ,181.5,182.8,180.2
XS GIS Cut Line= 4
2179931.14014918756037.5579994272179817.03709724756013.274236672
2179609.50644275755976.0894829772179516.63915932 755972.37479164
#Sta/Elev= 30
       0 1129.17    19.7 1123.92    35.7 1118.02    43.9 1113.62    52.1 1111.03
    68.5 1107.52    88.9 1104.82   101.2 1102.24   109.4 1099.78   129.7  1091.5
   137.9 1089.12     150 1087.97   206.9 1089.04  213.15  1088.1   219.1 1087.02
   223.2 1087.29  225.771088.118   231.3 1088.87   243.5 1088.38   247.6 1088.75
   255.7  1091.1   262.2 1092.28   292.3 1094.74   308.5 1096.94   324.3 1102.18
   344.8 1110.89   372.9 1119.82   400.9  1131.2   412.9 1134.74   420.4 1137.69
#Mann= 4 ,-1,0
       0     .05       0  176.66      .1       0  213.15    .045       0
  225.77      .1       0
Bank Sta=213.15,225.77
XS Rating Curve= 0 ,0
Exp/Cntr(USF)=0,0
Exp/Cntr=0.3,0.1

Type RM Length L Ch R = 1 ,1278    ,147,144.9,141.5
XS GIS Cut Line= 3
2179990.47310117755870.4648227042179637.42883648755811.289789702
2179539.52195513755813.852926724
#Sta/Elev= 30
       0 1140.42     2.3 1139.24    10.4 1131.77    14.5 1129.46    30.7 1128.73
    34.8 1127.15      51 1118.04    59.1  1114.3    75.3 1108.35    87.5 1104.88
   128.1 1098.84   144.3 1094.99   160.5 1089.38   164.6 1088.64   209.2 1087.26
   217.3 1086.03  224.961087.332   229.5 1088.24   261.9 1087.42   286.2 1088.52
   294.3 1089.59   305.3  1092.2   326.8 1094.28     339 1096.92   367.2 1099.15
   383.2 1102.47   411.2  1109.9   431.2 1118.53   447.3  1120.8   455.9  1123.7
#Mann= 5 ,-1,0
       0     .06       0      40     .05       0   209.2    .045       0
  224.96     .05       0     340      .1       0
Bank Sta=209.2,224.96
XS Rating Curve= 0 ,0
Exp/Cntr(USF)=0,0
Exp/Cntr=0.3,0.1

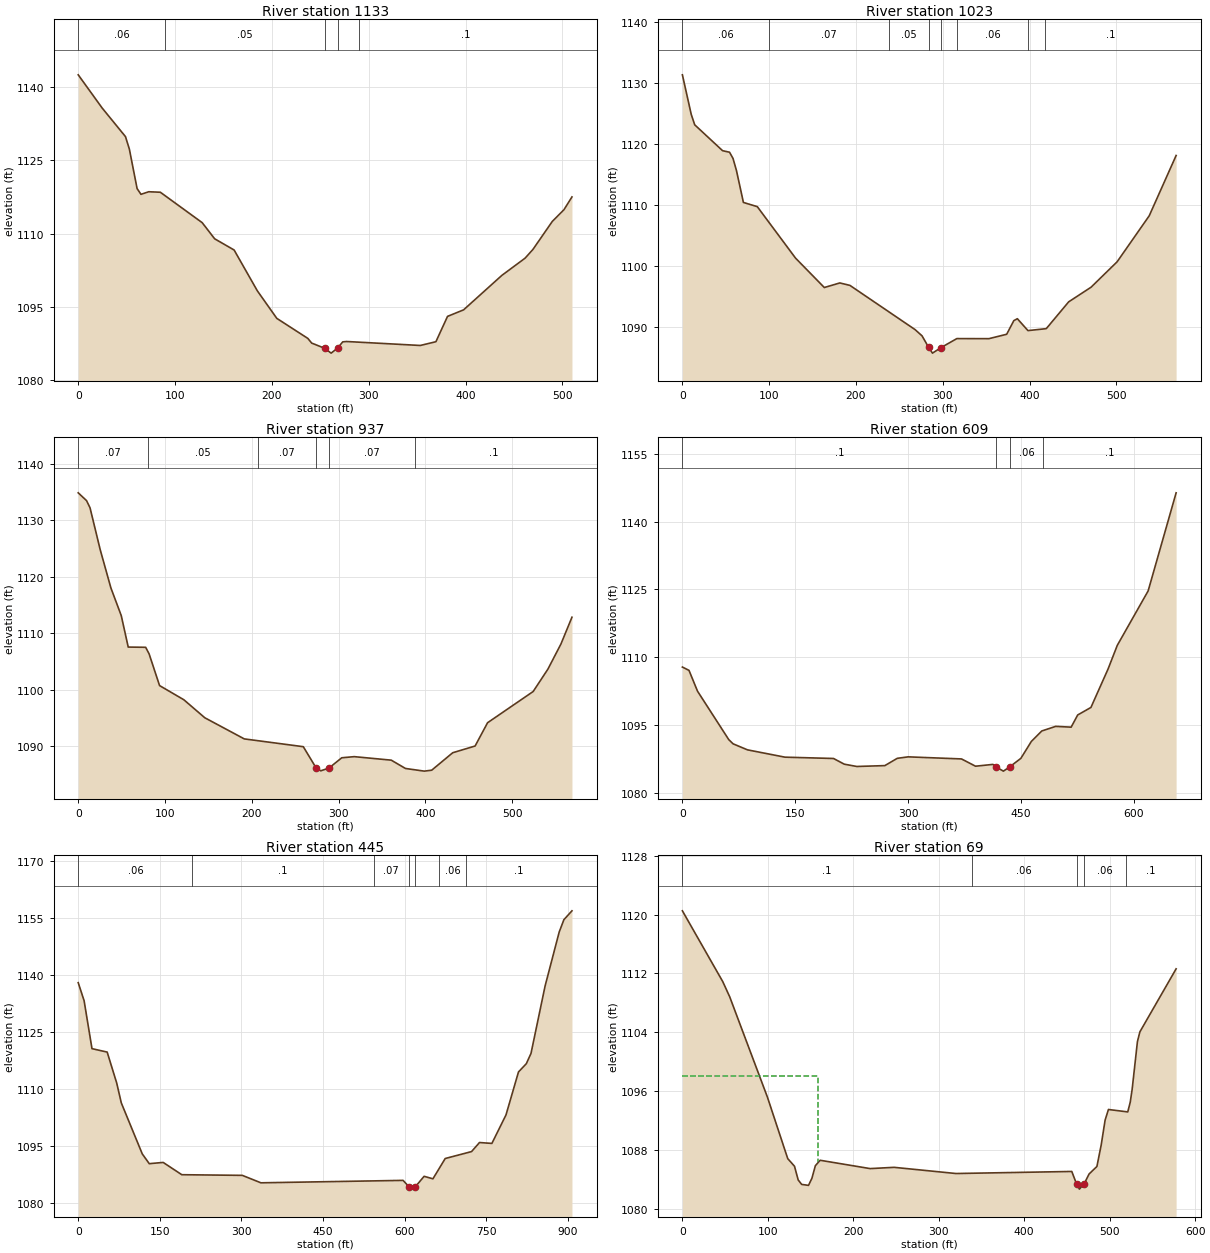
Type RM Length L Ch R = 1 ,1133    ,110.8,110.2,110.3
XS GIS Cut Line= 2
2180044.86069974755680.4567060772179535.94798654 755711.41246722
#Sta/Elev= 30
       0 1142.53    24.7 1135.73    48.8 1129.87    52.8 1127.32    60.8 1119.22
    64.8 1118.04    72.8 1118.57    84.8 1118.47     128 1112.24   140.9 1108.93
     161 1106.63     185 1098.26   205.1 1092.62   237.1 1088.52   241.1 1087.56
   254.4  1086.5   261.2  1085.5  267.821086.532   273.2 1087.81   277.2 1087.88
   353.3 1087.07   369.4 1087.84   381.4 1093.03     398 1094.37   437.5 1101.43
   461.5 1104.96   469.6 1106.75   489.6 1112.49   501.6 1114.88   509.9 1117.51
#Mann= 5 ,-1,0
       0     .06       0      90     .05       0   254.4    .045       0
  267.82     .05       0     290      .1       0
Bank Sta=254.4,267.82
XS Rating Curve= 0 ,0
Exp/Cntr(USF)=0,0
Exp/Cntr=0.3,0.1

Type RM Length L Ch R = 1 ,1023    ,85.4,85.4,85.4
XS GIS Cut Line= 6
2180054.36995803755541.0880044162179897.59597579755532.836742193
2179809.37094125755582.9790280092179771.92290501 755587.42201536
2179663.38707116755567.1112160422179512.96021371 755626.13947656
#Sta/Elev= 30
       0 1131.31    10.2 1124.82    14.2 1123.12    46.3 1118.88    54.3 1118.63
    58.3 1117.62    62.3 1115.62    70.3  1110.4    86.3 1109.71   130.4 1101.27
   163.5 1096.46   181.4 1097.21     193 1096.81     268 1089.57   276.1 1088.54
   283.71086.647   288.1 1085.71     298 1086.62   316.2 1088.09   353.1 1088.08
   373.6  1088.8   381.8 1091.03   385.9 1091.35   398.1  1089.4   419.2 1089.72
     445 1094.11   470.8 1096.51   500.8 1100.67   537.8 1108.21   568.8 1118.09
#Mann= 8 ,-1,0
       0     .06       0     100     .07       0  237.55     .05       0
   283.7    .045       0     298     .05       0  316.45     .06       0
  398.04     .07       0  417.19      .1       0
Bank Sta=283.7,298
XS Rating Curve= 0 ,0
Exp/Cntr(USF)=0,0
Exp/Cntr=0.3,0.1

Type RM Length L Ch R = 1 ,937     ,328.6,328.6,328.6
XS GIS Cut Line= 6
2180033.74180247755458.2580259482179876.96782023755450.006763725
 2179788.7427857755500.1490495412179751.29474946755504.592036892
 2179642.7589156755484.2812375742179492.33205815755543.309498091
#Sta/Elev= 30
       0 1134.84     9.6 1133.46    13.6 1132.19    25.3  1124.8    37.6 1118.04
    49.6 1113.11    57.6 1107.56    77.7 1107.52    81.7 1106.34    93.7 1100.75
   121.7 1098.24   145.8 1095.06   191.3 1091.32   259.3 1089.94  274.121086.169
   279.4 1085.67     289 1086.18   303.6 1087.98     318 1088.18   360.6 1087.56
     377 1086.09   398.6 1085.62   407.2 1085.78   431.4 1088.87   457.2 1090.06
   471.6 1094.18   524.1  1099.7   541.1 1103.66   556.1  1108.1   568.8 1112.84
#Mann= 6 ,-1,0
       0     .07       0      80     .05       0  206.99     .07       0
  274.12    .045       0     289     .07       0  388.04      .1       0
Bank Sta=274.12,289
XS Rating Curve= 0 ,0
Exp/Cntr(USF)=0,0
Exp/Cntr=0.3,0.1

Type RM Length L Ch R = 1 ,609     ,161.4,163.2,161.1
XS GIS Cut Line= 3
2179951.60353881755372.5990020592179653.28915888755290.708780117
2179354.24361626755466.187827135
#Sta/Elev= 30
       0 1107.82     8.8 1107.08    20.1 1102.48    61.6 1091.76    67.4 1090.82
    86.5 1089.49   136.3 1087.87   200.8 1087.58   215.1 1086.32   231.7 1085.81
     269    1086   285.5 1087.61     300 1087.94   370.9 1087.48   389.5 1085.87
   412.7 1086.27     417 1085.67   426.6 1084.78   434.7 1085.69   449.8 1087.61
   463.7 1091.35   477.6 1093.67   496.1 1094.69   516.6 1094.51   525.3 1097.21
   542.9 1098.88   565.7  1107.4   577.9 1112.62   618.9 1124.67   656.1 1146.39
#Mann= 4 ,-1,0
       0      .1       0     417    .045       0   434.7     .06       0
  479.35      .1       0
Bank Sta=417,434.7
XS Rating Curve= 0 ,0
Exp/Cntr(USF)=0,0
Exp/Cntr=0.3,0.1

Type RM Length L Ch R = 1 ,445     ,369.3,376.9,366
XS GIS Cut Line= 4
2180054.29145542755267.6625125512179661.36429092755118.953897783
2179565.18853778755177.9044432952179255.85065728755389.448939601
#Sta/Elev= 30
       0    1138    10.8 1133.26    25.3 1120.65    53.2 1119.75    70.7 1111.64
    79.2 1106.39   117.7 1092.99   130.6 1090.41   156.2 1090.74   190.4 1087.51
   301.6 1087.34   335.9 1085.38   597.2 1086.02607.97161084.358   613.7 1083.72
620.05161084.401   635.9 1087.09   652.1 1086.43   674.7 1091.77   723.1 1093.59
   737.7 1095.97   760.5 1095.74   786.4 1103.22   809.4 1114.53   823.8  1116.7
   832.4  1119.4   858.3 1137.12   884.2  1151.3   892.9 1154.57   907.7 1156.89
#Mann= 7 ,-1,0
       0     .06       0     210      .1       0  542.93     .07       0
607.9716    .045       0620.0516     .07       0  662.93     .06       0
  712.93      .1       0
Bank Sta=607.9716,620.0516
XS Rating Curve= 0 ,0
Exp/Cntr(USF)=0,0
Exp/Cntr=0.3,0.1

Type RM Length L Ch R = 1 ,69      ,799.5,,824.6
XS GIS Cut Line= 3
2179395.63056271754741.9496429942179413.88468127 755010.05700934
2179187.24346079755220.182822315
#Sta/Elev= 30
       0 1120.51    47.3 1110.88    55.4 1108.82    99.5  1095.2   123.3 1086.84
   131.2 1085.81   135.5 1083.95   139.6 1083.34   147.6 1083.21   151.6 1084.18
   155.6 1085.88   161.2 1086.62   219.7 1085.49   247.8 1085.66   320.2 1084.82
   455.7  1085.1  461.231083.418   464.6  1082.7   470.3 1083.44   475.9 1084.75
   485.1 1085.78   490.1 1088.69   494.7 1092.08   498.6 1093.52   521.2 1093.19
   524.1 1094.51   526.3 1096.22   532.5 1102.73   535.4 1104.07   577.8 1112.63
#Mann= 5 ,-1,0
       0      .1       0  338.73     .06       0  461.23    .045       0
   470.3     .06       0  518.73      .1       0
#XS Ineff= 2 , 0
          159.08 1098.09
Permanent Ineff=
       F       F
Bank Sta=461.23,470.3
XS Rating Curve= 0 ,0
Exp/Cntr(USF)=0,0
Exp/Cntr=0.3,0.1
LCMann Table=0

Chan Stop Cuts=-1
Use User Specified Reach Order=0
Composite Channel Slope=5